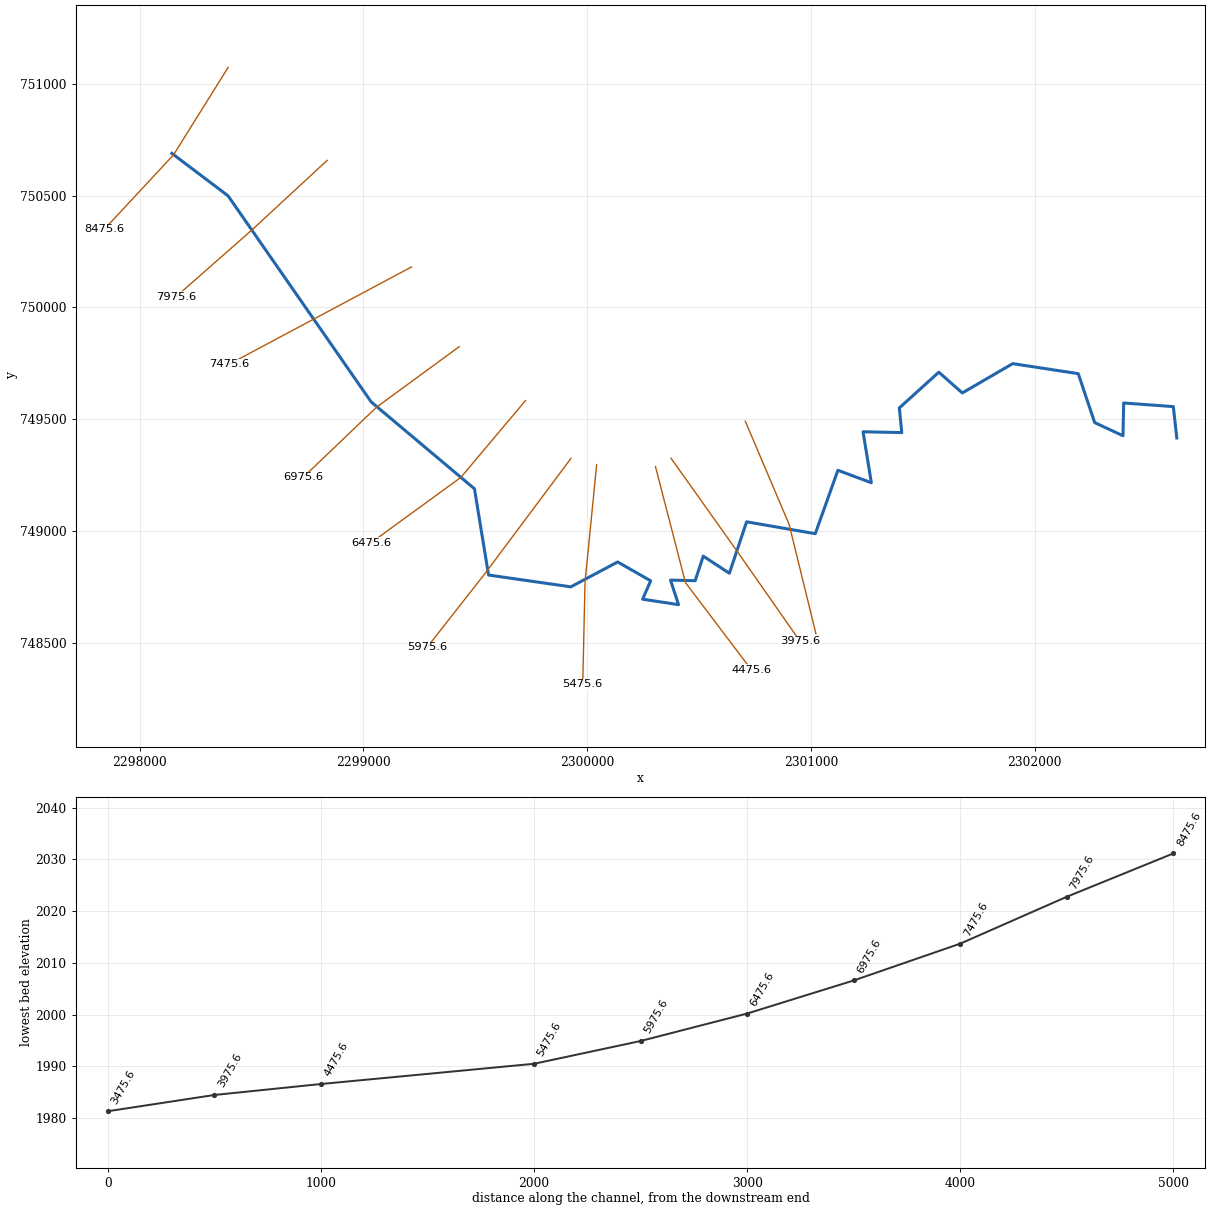
--- CAMPFLDRN.prj (project) ---

Proj Title=CAMPFLDRN
Current Plan=p01
Geom File=g01
Flow File=f01
Plan File=p01
DSS Export Rating Curves=0
DSS Export Rating Curve Sorted=0
DSS Export Volume Flow Curves=0
DXF OffsetX=0
DXF OffsetY=0
DXF ScaleX=0
DXF ScaleY=0

--- CAMPFLDRN.p01 (plan) ---

Plan Title=Floodplain
Program Version=4.00
Geom File=g01
Flow File=f01
K Sum by GR=0
Std Step Tol=0.01
Critical Tol=0.01
Num of Std Step Trials=20
Max Error Tol=0.3
Flow Tol Ratio=0.001
Split Flow NTrial=30
Split Flow Tol=0.02
Split Flow Ratio=0.02
Log Output Level=0
Friction Slope Method=1
Unsteady Friction Slope Method=2
Unsteady Bridges Friction Slope Method=1
Global Log Level=0
CheckData=False
Run HTab=0
Run UNet=0
Run PostProcess=0
UNET Theta=0
UNET Theta Warmup=0
UNET ZTol=0
UNET ZSATol=0
UNET MxIter=0
UNET MaxInSteps=0
UNET DtIC=0
UNET DtMin=0
UNET MaxCRTS=0
UNET WFStab=0
UNET SFStab=0
UNET WFX=0
UNET SFX=0
UNET DSS MLevel=0
UNET DZMax Abort=0
UNET Convert EG Bridges=0
UNET Use Existing IB Tables=0
UNET Froude Limit=0
UNET Froude Power=0
Write IC File=0
Echo Input=False
Echo Output=False
Write Detailed=0

--- CAMPFLDRN.f01 (steady flow) ---

Flow Title=Flow
Program Version=4.00
Number of Profiles=1
Profile Names=P100yr
River Rch & RM=CAMPFLDRN,Main      ,8475.6
296.1640
River Rch & RM=CAMPFLDRN,Main      ,7475.6
307.5971
River Rch & RM=CAMPFLDRN,Main      ,7475.6
298.9043
River Rch & RM=CAMPFLDRN,Main      ,6975.6
323.5284
River Rch & RM=CAMPFLDRN,Main      ,6975.6
312.2601
River Rch & RM=CAMPFLDRN,Main      ,6475.6
324.7215
River Rch & RM=CAMPFLDRN,Main      ,5975.6
356.7247
River Rch & RM=CAMPFLDRN,Main      ,5975.6
328.7504
River Rch & RM=CAMPFLDRN,Main      ,5475.6
359.8219
River Rch & RM=CAMPFLDRN,Main      ,5475.6
358.6328
River Rch & RM=CAMPFLDRN,Main      ,4475.6
363.5053
River Rch & RM=CAMPFLDRN,Main      ,4475.6
362.9211
River Rch & RM=CAMPFLDRN,Main      ,4475.6
362.3192
River Rch & RM=CAMPFLDRN,Main      ,3975.6
365.8135
River Rch & RM=CAMPFLDRN,Main      ,3975.6
364.9865
River Rch & RM=CAMPFLDRN,Main      ,3475.6
366.7011
Boundary for River Rch & Prof#=CAMPFLDRN,Main      ,1
Up Type=0
Dn Type=3
Dn Slope=0.004812

--- CAMPFLDRN.g01 (geometry) ---

Geom Title=Geometry
Program Version=4.00

River Reach=CAMPFLDRN     ,Main
Reach XY= 30
     2298144.211      750690.075     2298395.253      750499.971
     2299034.836      749577.054     2299496.207      749188.469
     2299559.141      748802.185     2299926.763      748749.233
     2300136.138      748860.692     2300283.534      748776.316
     2300247.596      748694.025     2300408.013      748669.546
     2300372.075      748779.441     2300482.492      748776.837
     2300518.429      748886.733     2300635.096      748810.171
     2300712.180      749040.379     2301018.950      748987.254
     2301119.992      749271.108     2301269.471      749215.379
     2301232.492      749443.504     2301405.409      749439.858
     2301394.471      749550.275     2301570.989      749710.312
     2301676.017      749617.408     2301900.992      749748.562
     2302193.885      749703.806     2302267.380      749484.663
     2302393.831      749425.645     2302396.802      749572.446
     2302618.686      749556.242     2302634.294      749415.767

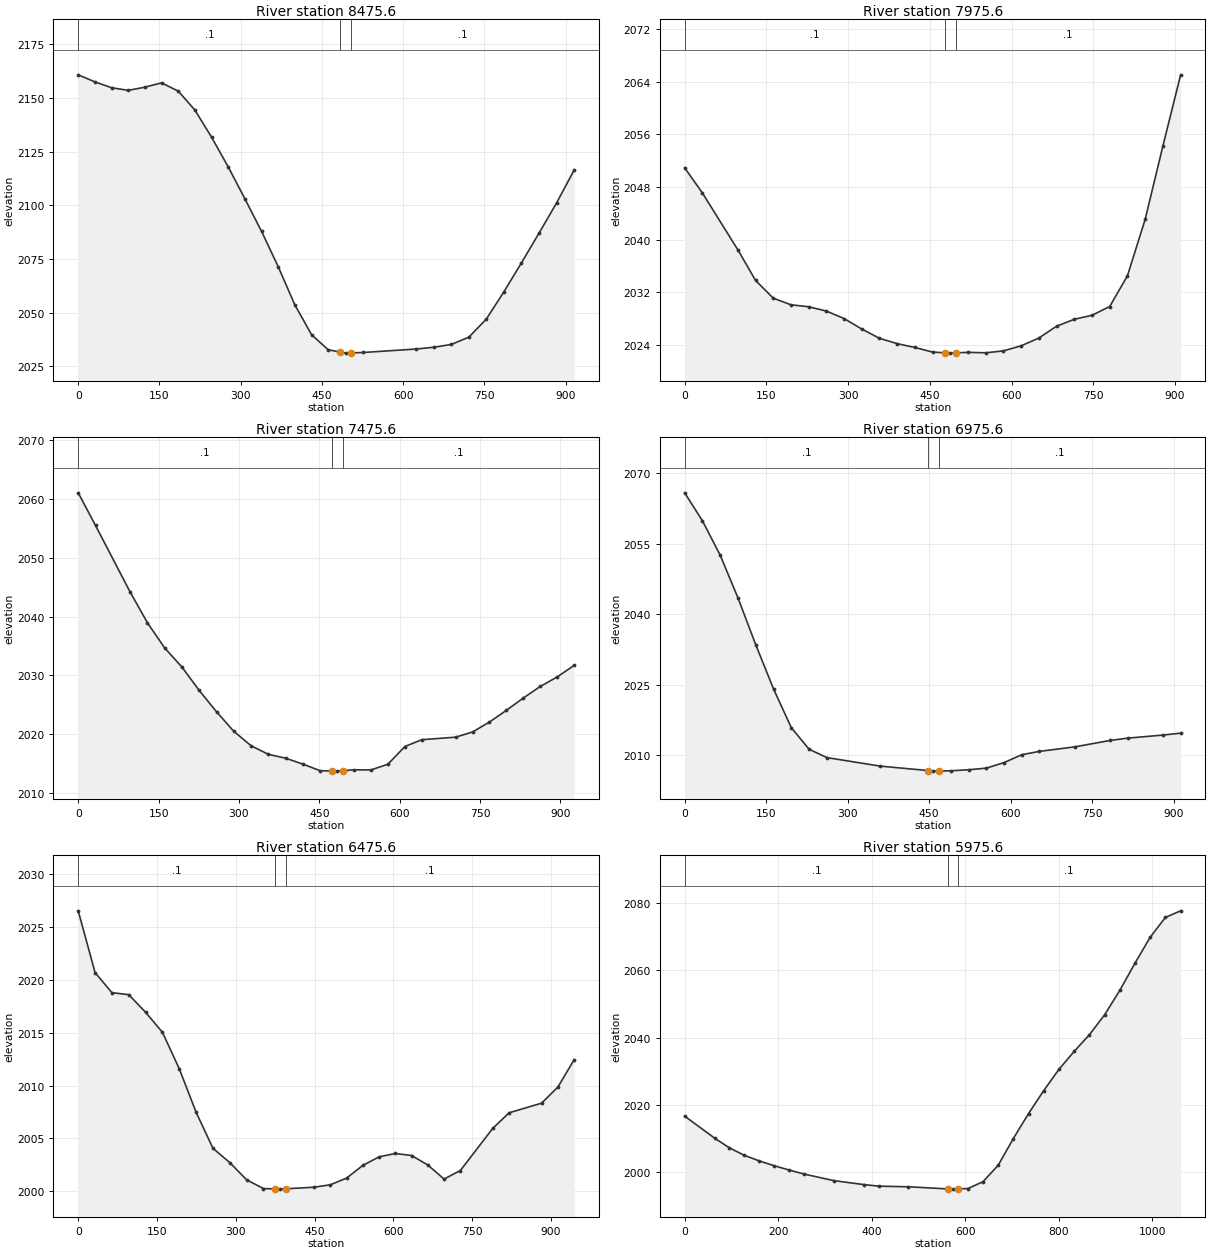
Type RM Length L Ch R = 1 ,8475.6,506.3,500,497
XS GIS Cut Line= 3
     2298395.909      751075.361     2298151.779      750683.539
     2297842.793      750350.676
#Sta/Elev= 30
       0 2160.85    30.8 2157.56    61.6 2154.84    92.3 2153.61   123.1 2155.09
   153.9 2157.10   184.7 2153.26   215.4 2144.46   246.2 2131.80   277.0 2117.94
   307.8 2103.06   338.6 2087.87   369.3 2071.44   400.1 2053.60   430.9 2039.75
   461.6 2032.72   484.1 2031.63   494.1 2031.15   504.1 2031.24   526.5 2031.45
   623.9 2033.06   656.3 2033.88   688.7 2035.18   721.2 2038.56   753.6 2047.00
   786.1 2059.74   818.5 2073.23   850.9 2087.05   883.4 2101.17   915.8 2116.46
#Mann= 3 , 0 , 0
       0     0.1       0   484.1   0.045       0   504.1     0.1       0
Bank Sta=484.1,504.1
Exp/Cntr=0.3,0.1

Type RM Length L Ch R = 1 ,7975.6,506.2,500,493.9
XS GIS Cut Line= 3
     2298838.148      750658.848     2298504.536      750349.498
     2298163.026      750048.549
#Sta/Elev= 30
       0 2050.92    32.5 2047.10    97.5 2038.48   130.0 2033.83   162.5 2031.13
   195.0 2030.12   227.5 2029.82   260.0 2029.17   292.5 2028.03   325.0 2026.44
   357.5 2025.03   390.0 2024.22   422.5 2023.64   455.0 2022.94   477.5 2022.83
   487.5 2022.78   497.5 2022.82   520.0 2022.90   552.5 2022.83   585.0 2023.12
   617.5 2023.89   650.0 2025.07   682.6 2026.87   715.1 2027.92   747.6 2028.53
   780.1 2029.86   812.6 2034.52   845.1 2043.08   877.6 2054.20   910.2 2065.04
#Mann= 3 , 0 , 0
       0     0.1       0   477.5   0.045       0   497.5     0.1       0
Bank Sta=477.5,497.5
Exp/Cntr=0.3,0.1

Type RM Length L Ch R = 1 ,7475.6,495.7,500,506.8
XS GIS Cut Line= 3
     2299214.483      750181.258     2298816.170      749968.356
     2298398.289      749745.011
#Sta/Elev= 30
       0 2061.09    32.3 2055.53    96.8 2044.22   129.0 2039.00   161.3 2034.69
   193.6 2031.43   225.8 2027.45   258.1 2023.83   290.3 2020.50   322.6 2018.04
   354.9 2016.58   387.1 2015.92   419.4 2014.91   451.6 2013.79   473.2 2013.74
   483.2 2013.72   493.2 2013.79   514.8 2013.94   546.4 2013.93   578.0 2014.89
   609.6 2017.91   641.2 2019.07   704.4 2019.50   735.9 2020.38   767.5 2022.08
   799.1 2024.07   830.7 2026.17   862.3 2028.13   893.9 2029.76   925.5 2031.72
#Mann= 3 , 0 , 0
       0     0.1       0   473.2   0.045       0   493.2     0.1       0
Bank Sta=473.2,493.2
Exp/Cntr=0.3,0.1

Type RM Length L Ch R = 1 ,6975.6,494.7,500,495.4
XS GIS Cut Line= 3
     2299428.343      749824.735     2299059.062      749553.870
     2298730.514      749239.150
#Sta/Elev= 24
       0 2065.80    32.7 2059.85    65.4 2052.52    98.1 2043.45   130.8 2033.49
   163.6 2024.07   196.3 2015.84   229.0 2011.26   261.7 2009.48   359.8 2007.67
     448 2006.72   458.0 2006.60     468 2006.62   490.5 2006.67   523.0 2006.90
   555.5 2007.24   588.0 2008.42   620.5 2010.09   653.0 2010.80   718.0 2011.76
   782.9 2013.12   815.4 2013.62   880.4 2014.27   912.9 2014.68
#Mann= 3 , 0 , 0
       0     0.1       0     448   0.045       0     468     0.1       0
Bank Sta=448,468
Exp/Cntr=0.3,0.1

Type RM Length L Ch R = 1 ,6475.6,492.6,500,508.4
XS GIS Cut Line= 3
     2299724.075      749582.979     2299435.449      749239.288
     2299035.292      748947.524
#Sta/Elev= 30
       0 2026.53    32.1 2020.69    64.1 2018.79    96.2 2018.60   128.2 2016.94
   160.3 2015.04   192.4 2011.59   224.4 2007.48   256.5 2004.07   288.5 2002.72
   320.6 2001.09   352.6 2000.26   374.7 2000.23   384.7 2000.21   394.7 2000.24
   448.8 2000.39   479.8 2000.62   510.7 2001.25   541.7 2002.45   572.6 2003.26
   603.6 2003.58   634.5 2003.39   665.5 2002.49   696.4 2001.16   727.4 2001.97
   789.3 2005.97   820.2 2007.43   882.1 2008.34   913.1 2009.87   944.0 2012.45
#Mann= 3 , 0 , 0
       0     0.1       0   374.7   0.045       0   394.7     0.1       0
Bank Sta=374.7,394.7
Exp/Cntr=0.3,0.1

Type RM Length L Ch R = 1 ,5975.6,487.5,500,514.1
XS GIS Cut Line= 3
     2299927.171      749324.022     2299546.019      748812.454
     2299285.498      748479.563
#Sta/Elev= 30
       0 2016.62    63.8 2010.10    95.7 2007.19   127.6 2004.96   159.5 2003.29
   191.4 2001.87   223.3 2000.59   255.2 1999.39   319.0 1997.43   382.8 1996.26
   414.7 1995.78   478.5 1995.60   564.2 1994.95   574.2 1994.90   584.2 1994.96
   606.0 1995.08   638.0 1997.11   670.5 2002.00   703.0 2009.97   735.5 2017.40
   768.0 2024.24   800.5 2030.57   833.0 2035.89   865.6 2040.85   898.1 2046.79
   930.6 2054.05   963.1 2062.16   995.6 2069.86  1028.2 2075.79  1060.7 2077.74
#Mann= 3 , 0 , 0
       0     0.1       0   564.2   0.045       0   584.2     0.1       0
Bank Sta=564.2,584.2
Exp/Cntr=0.3,0.1

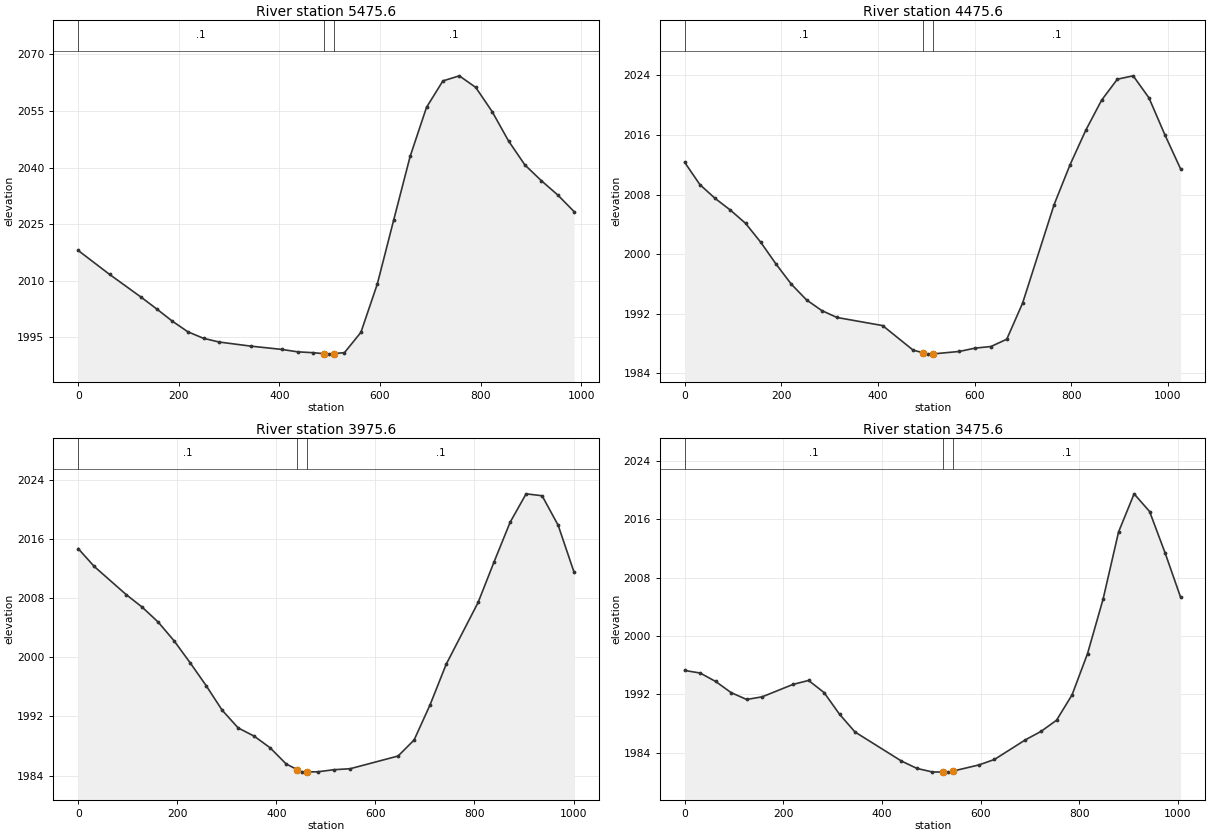
Type RM Length L Ch R = 1 ,5475.6,708.4,1000,783.3
XS GIS Cut Line= 3
     2300042.198      749295.981     2299990.158      748769.021
     2299980.006      748312.489
#Sta/Elev= 30
       0 2018.00    62.3 2011.66   124.6 2005.66   155.7 2002.53   186.9 1999.27
   218.0 1996.43   249.2 1994.69   280.3 1993.71   342.6 1992.63   404.9 1991.75
   436.1 1991.11   467.2 1990.88   488.4 1990.62   498.4 1990.50   508.4 1990.63
   529.5 1990.90   562.1 1996.27   594.8 2009.11   627.4 2026.11   660.0 2042.94
   692.6 2055.97   725.2 2062.99   757.8 2064.34   790.5 2061.27   823.1 2054.86
   855.7 2047.07   888.3 2040.69   920.9 2036.53   953.6 2032.73   986.2 2028.30
#Mann= 3 , 0 , 0
       0     0.1       0   488.4   0.045       0   508.4     0.1       0
Bank Sta=488.4,508.4
Exp/Cntr=0.3,0.1

Type RM Length L Ch R = 1 ,4475.6,504.6,500,502.7
XS GIS Cut Line= 3
     2300305.171      749287.276     2300438.881      748768.399
     2300734.491      748376.702
#Sta/Elev= 30
       0 2012.33    31.5 2009.34    63.0 2007.49    94.6 2005.92   126.1 2004.14
   157.6 2001.59   189.1 1998.68   220.6 1995.99   252.2 1993.87   283.7 1992.44
   315.2 1991.51   409.8 1990.42   472.8 1987.13   494.3 1986.76   504.3 1986.59
   514.3 1986.62   568.5 1986.95   601.3 1987.40   634.0 1987.61   666.7 1988.59
   699.4 1993.42   764.8 2006.67   797.6 2011.99   830.3 2016.64   863.0 2020.67
   895.7 2023.49   928.4 2023.94   961.1 2020.98   993.8 2016.06  1026.6 2011.44
#Mann= 3 , 0 , 0
       0     0.1       0   494.3   0.045       0   514.3     0.1       0
Bank Sta=494.3,514.3
Exp/Cntr=0.3,0.1

Type RM Length L Ch R = 1 ,3975.6,339.3,500,413.2
XS GIS Cut Line= 3
     2300374.384      749325.274     2300673.224      748903.835
     2300950.365      748506.280
#Sta/Elev= 30
       0 2014.70    32.3 2012.29    96.9 2008.48   129.2 2006.78   161.4 2004.77
   193.7 2002.22   226.0 1999.26   258.3 1996.17   290.6 1992.85   322.9 1990.45
   355.2 1989.34   387.5 1987.76   419.8 1985.58   442.1 1984.81   452.1 1984.47
   462.1 1984.49   484.4 1984.52   516.6 1984.80   549.0 1984.93   645.9 1986.65
   678.2 1988.82   710.5 1993.59   742.8 1999.04   807.4 2007.42   839.7 2012.92
   872.0 2018.26   904.3 2022.11   936.6 2021.85   969.0 2017.86  1001.3 2011.47
#Mann= 3 , 0 , 0
       0     0.1       0   442.1   0.045       0   462.1     0.1       0
Bank Sta=442.1,462.1
Exp/Cntr=0.3,0.1

Type RM Length L Ch R = 1 ,3475.6,3341.1,3475.6,3205.1
XS GIS Cut Line= 3
     2300706.227      749490.848     2300902.317      749028.387
     2301021.871      748539.574
#Sta/Elev= 30
       0 1995.28    31.4 1994.93    62.8 1993.77    94.2 1992.24   125.6 1991.30
   157.0 1991.66   219.8 1993.37   251.2 1993.91   282.6 1992.25   314.0 1989.27
   345.3 1986.84   439.5 1982.85   470.9 1981.84   502.3 1981.35   523.8 1981.34
   533.8 1981.33   543.8 1981.47   596.7 1982.32   628.1 1983.07   691.0 1985.77
   722.5 1986.92   753.9 1988.45   785.4 1991.93   816.8 1997.60   848.3 2005.07
   879.7 2014.29   911.2 2019.52   942.6 2017.09   974.1 2011.40  1005.5 2005.32
#Mann= 3 , 0 , 0
       0     0.1       0   523.8   0.045       0   543.8     0.1       0
Bank Sta=523.8,543.8
Exp/Cntr=0.3,0.1